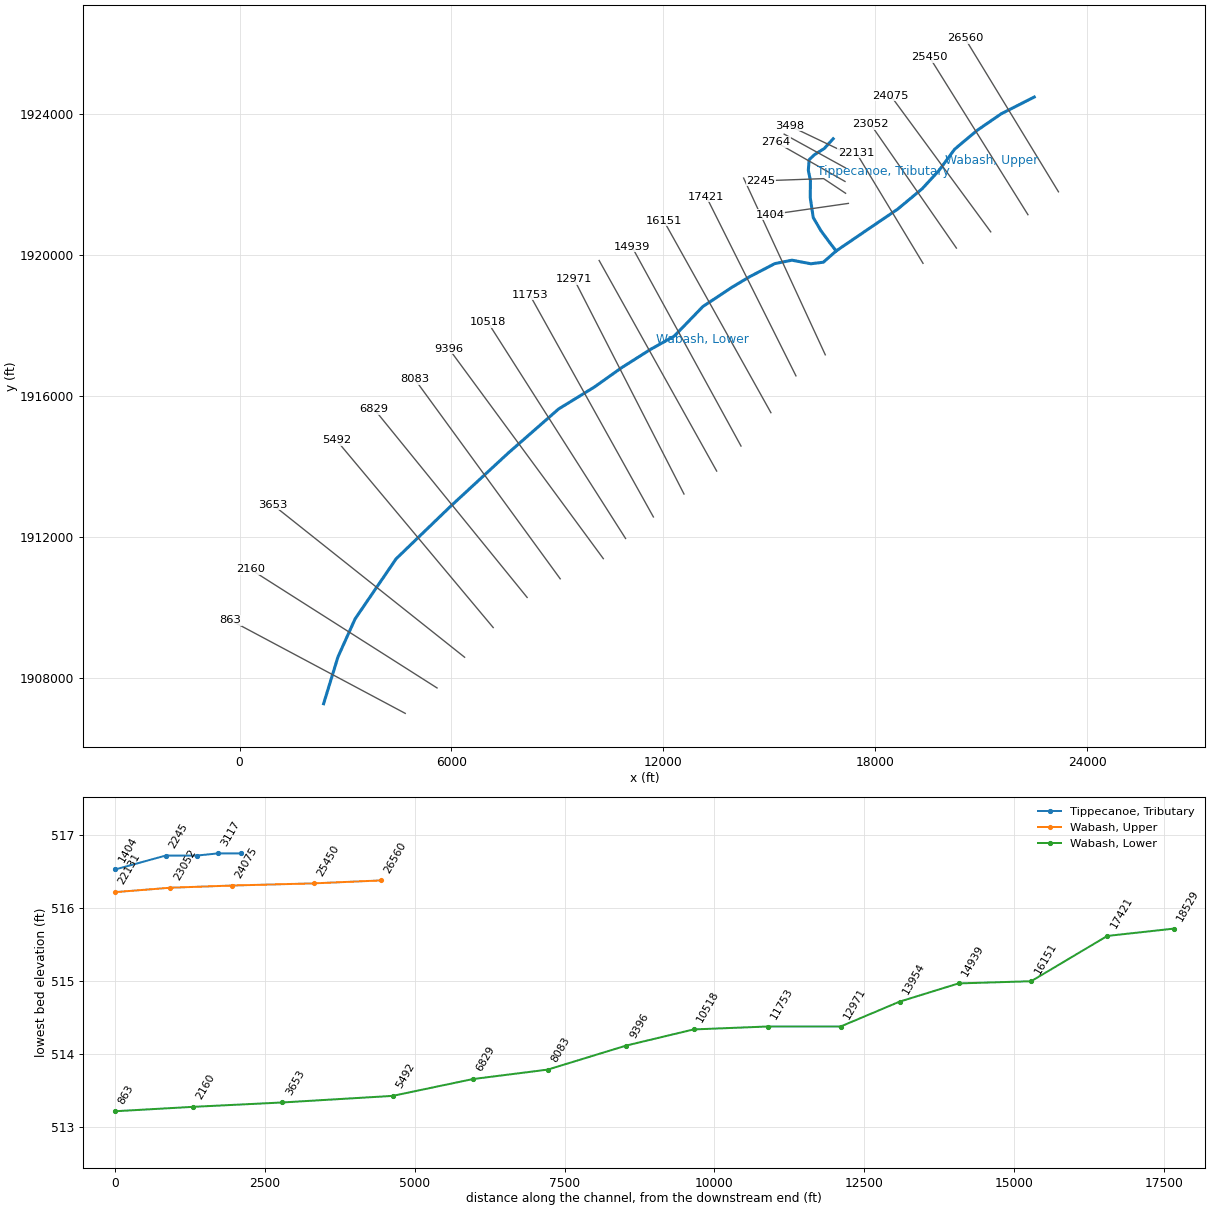
--- 1D_model.prj (project) ---

Proj Title=1D_model
Current Plan=p01
Default Exp/Contr=0.3,0.1
English Units
Geom File=g01
Flow File=f01
Plan File=p01
Y Axis Title=Elevation
X Axis Title(PF)=Main Channel Distance
X Axis Title(XS)=Station
BEGIN DESCRIPTION:
END DESCRIPTION:
DSS Export Rating Curves= 0
DSS Export Rating Curve Sorted= 0
DSS Export Volume Flow Curves= 0
DXF OffsetX= 0
DXF OffsetY= 0
DXF ScaleX= 1
DXF ScaleY= 10

--- 1D_model.p01 (plan) ---

Plan Title=1D_model
Program Version=5.05
Short Identifier=SteadyFlow
Geom File=g01
Flow File=f01
Supercritical Flow
K Sum by GR= 0
Std Step Tol= 0.01
Critical Tol= 0.01
Num of Std Step Trials= 20
Max Error Tol= 0.3
Flow Tol Ratio= 0.001
Split Flow NTrial= 30
Split Flow Tol= 0.02
Split Flow Ratio= 0.02
Log Output Level= 0
Friction Slope Method= 1
Unsteady Friction Slope Method= 2
Unsteady Bridges Friction Slope Method= 1
Parabolic Critical Depth
Global Vel Dist= 0 , 0 , 0
Global Log Level= 0
CheckData=True
Encroach Param=-1 ,0,0, 0
Computation Interval=1MIN
Output Interval=1HOUR
Instantaneous Interval=1HOUR
Mapping Interval=1HOUR
Computation Time Step Use Courant=        0
Computation Time Step Use Time Series=    0
Computation Time Step Count To Double=0
Computation Time Step Max Doubling=0
Computation Time Step Max Halving=0
Computation Time Step Residence Courant=0
Run HTab= 0
Run UNet= 0
Run Sediment= 0
Run PostProcess= 0
Run WQNet= 0
Run RASMapper= 0
UNET Theta= 1
UNET Theta Warmup= 1
UNET ZTol= 0.02
UNET ZSATol= 0.02
UNET MxIter= 20
UNET Max Iter WO Improvement= 0
UNET MaxInSteps= 0
UNET DtIC= 0
UNET DtMin= 0
UNET MaxCRTS= 20
UNET WFStab= 2
UNET SFStab= 1
UNET WFX= 1
UNET SFX= 1
UNET 1D Methodology=Finite Difference
UNET DSS MLevel= 4
UNET Pardiso=0
UNET DZMax Abort= 100
UNET Use Existing IB Tables=-1
UNET Froude Reduction=False
UNET Froude Limit= 0.8
UNET Froude Power= 4
UNET D1 Cores= 0
UNET D2 Coriolis=0
UNET D2 Cores= 0
UNET D2 Theta= 1
UNET D2 Theta Warmup= 1
UNET D2 Z Tol= 0.01
UNET D2 Volume Tol= 0.01
UNET D2 Max Iterations= 20
UNET D2 Equation= 0
UNET D2 RampUpFraction=0.1
UNET D2 TimeSlices= 1
UNET D2 BCVolumeCheck=0
UNET D1D2 MaxIter= 0
UNET D1D2 ZTol=0.01
UNET D1D2 QTol=0.1
UNET D1D2 MinQTol=1
Write IC File= 0
Write IC File at Fixed DateTime=0
Write IC File at Sim End=0
Echo Input=False
Echo Parameters=False
Echo Output=False
Write Detailed= 0
HDF Write Warmup=0
HDF Write Time Slices=0
HDF Flush=0
HDF Face Node Velocities=0
HDF Compression= 1
HDF Chunk Size= 1
HDF Spatial Parts= 1
HDF Use Max Rows=0
HDF Fixed Rows= 1
Calibration Method= 0
Calibration Iterations= 20
Calibration Max Change=0.05
Calibration Tolerance=0.2
Calibration Maximum=1.5
Calibration Minimum=0.5
Calibration Optimization Method= 1
WQ AD Non Conservative
WQ ULTIMATE=-1
WQ Max Comp Step=1HOUR
WQ Output Interval=15MIN
WQ Output Selected Increments= 0
WQ Output face flow=0
WQ Output face velocity=0
WQ Output face area=0
WQ Output face dispersion=0
WQ Output cell volume=0
WQ Output cell surface area=0
WQ Output cell continuity=0
WQ Output cumulative cell continuity=0
WQ Output face conc=0
WQ Output face dconc_dx=0
WQ Output face courant=0
WQ Output face peclet=0
WQ Output face adv mass=0
WQ Output face disp mass=0
WQ Output cell mass=0
WQ Output cell source sink temp=0
WQ Output nsm pathways=0
WQ Output nsm derived pathways=0
WQ Output MaxMinRange=-1
WQ Daily Max Min Mean=-1
WQ Daily Range=0
WQ Daily Time=0
WQ Create Restart=0
WQ Fixed Restart=0
WQ System Summary=0
WQ Write To DSS=0
WQ Use Fixed Temperature=0
Sorting and Armoring Iterations= 10
XS Update Threshold= 0.02
Bed Roughness Predictor= 0
Hydraulics Update Threshold= 0.02
Energy Slope Method= 1
Volume Change Method= 1
Sediment Retention Method= 0
XS Weighting Method= 0
Number of US Weighted Cross Sections= 1
Number of DS Weighted Cross Sections= 1
Upstream XS Weight=0
Main XS Weight=1
Downstream XS Weight=0
Number of DS XS's Weighted with US Boundary= 1
Upstream Boundary Weight= 1
Weight of XSs Associated with US Boundary= 0
Number of US XS's Weighted with DS Boundary= 1
Downstream Boundary Weight= 0.5
Weight of XSs Associated with DS Boundary= 0.5
Percentile Method= 0
Sediment Output Level= 3
Mass or Volume Output= 0
Output Increment Type= 1
Profile and TS Output Increment= 1
XS Output Flag= 0
XS Output Increment= 10
Write Gradation File= 0
Read Gradation Hotstart= 0
Write HDF5 File= 1
Write Binary Output= 1
Write DSS Sediment File= 0
SV Curve= 0
Specific Gage Flag= 0

--- 1D_model.f01 (steady flow) ---

Flow Title=1D_model
Program Version=5.05
Number of Profiles= 3
Profile Names=PF 1,PF 2,PF 3
River Rch & RM=Tippecanoe,Tributary       ,3498
   14000   21000   28000
River Rch & RM=Wabash,Upper           ,26560
   28000   40000   60000
River Rch & RM=Wabash,Lower           ,18529
   42000   61000   88000
Boundary for River Rch & Prof#=Tippecanoe,Tributary       , 1
Up Type= 2
Dn Type= 0
Boundary for River Rch & Prof#=Tippecanoe,Tributary       , 2
Up Type= 2
Dn Type= 0
Boundary for River Rch & Prof#=Tippecanoe,Tributary       , 3
Up Type= 2
Dn Type= 0
Boundary for River Rch & Prof#=Wabash,Upper           , 1
Up Type= 2
Dn Type= 0
Boundary for River Rch & Prof#=Wabash,Upper           , 2
Up Type= 2
Dn Type= 0
Boundary for River Rch & Prof#=Wabash,Upper           , 3
Up Type= 2
Dn Type= 0
Boundary for River Rch & Prof#=Wabash,Lower           , 1
Up Type= 0
Dn Type= 3
Dn Slope=0.002
Boundary for River Rch & Prof#=Wabash,Lower           , 2
Up Type= 0
Dn Type= 3
Dn Slope=0.002
Boundary for River Rch & Prof#=Wabash,Lower           , 3
Up Type= 0
Dn Type= 3
Dn Slope=0.002
DSS Import GetInterval= 0
DSS Import GetPeak= 0
DSS Import FillOption= 0

--- 1D_model.g01 (geometry) ---

Geom Title=1D_model
Program Version=5.05

Junct Name=Junction 1
Junct Desc=, 0 , 0 , 0 ,0
Up River,Reach=Wabash          ,Upper
Up River,Reach=Tippecanoe      ,Tributary
Dn River,Reach=Wabash          ,Lower
Junc L&A=0,0
Junc L&A=0,0

River Reach=Tippecanoe      ,Tributary
Reach XY= 11
16810.53903294191923289.6362541116556.9589831454 1923012.7998034
16286.61925381531922842.5858997516131.42422401471922697.40345252
16106.39276759531922397.02597549 16166.4682630021922101.65478974
16161.4619717181 1921616.044535216246.5689235442 1921055.3399114
16466.84574003541920679.8680651116707.14772166211920354.45913166
16892.69306981611920110.47412251

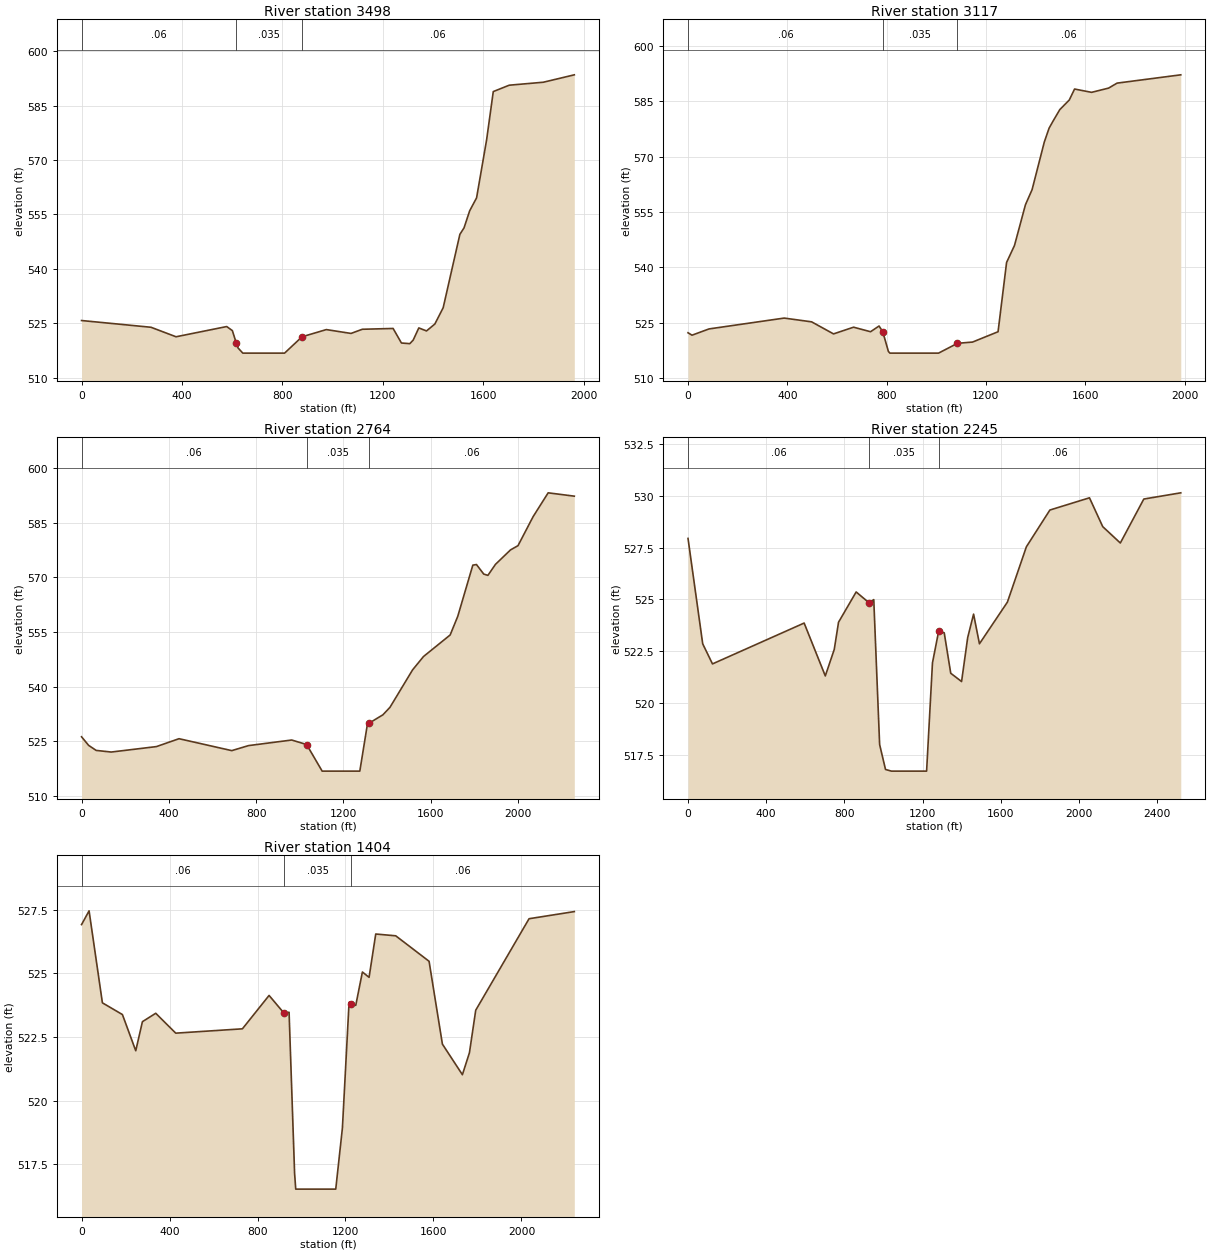
Type RM Length L Ch R = 1 ,3498    ,388.4,381.1,296.3
XS GIS Cut Line= 2
17337.32628449121922814.3482260615566.5182256303 1923659.8691911
#Sta/Elev= 30
       0  525.74   276.6  523.88   376.3  521.26   578.1  524.08   600.6  522.95
   615.6519.6588   623.1  518.18   642.3  516.75   808.5  516.75   877.9521.2508
   974.7  523.24  1073.1  522.18  1118.1  523.33  1240.7  523.55  1273.9  519.54
  1307.2  519.36  1320.6  520.33  1343.1   523.7  1373.7  522.87  1406.9  524.77
  1440.1  529.27  1506.6   549.5  1523.1  551.28  1545.6  555.99  1573.1  559.56
  1613.1  575.57  1639.6  588.87  1703.1  590.63  1839.1  591.45  1962.3  593.49
#Mann= 3 , 0 , 0
       0     .06       0   615.6    .035       0   877.9     .06       0
Bank Sta=615.6,877.9
XS Rating Curve= 0 ,0
Exp/Cntr(USF)=0,0
Exp/Cntr=0.3,0.1

Type RM Length L Ch R = 1 ,3117    ,356,353.1,318.8
XS GIS Cut Line= 2
17161.84080118071922463.3772594415422.93919383081923420.57080477
#Sta/Elev= 30
       0  522.27    16.1  521.61    84.6  523.31   387.4  526.25   497.9  525.23
   586.2  521.96   666.8  523.78   735.2  522.55   769.5   524.1   784.5522.5516
   807.1  517.22   813.1  516.75  1009.2  516.75  1085.2519.4056  1146.2  519.75
  1248.9  522.55  1283.2  541.32  1315.1  545.94  1359.2  556.97  1385.9  561.05
  1435.2  573.98  1454.4  577.72  1469.7  579.56  1497.5  582.75  1535.9  585.38
  1557.1  588.34  1625.6  587.44  1694.1  588.59  1728.3  589.94  1984.9  592.19
#Mann= 3 , 0 , 0
       0     .06       0   784.5    .035       0  1085.2     .06       0
Bank Sta=784.5,1085.2
XS Rating Curve= 0 ,0
Exp/Cntr(USF)=0,0
Exp/Cntr=0.3,0.1

Type RM Length L Ch R = 1 ,2764    ,326.9,519.2,1028.7
XS GIS Cut Line= 2
17145.88757542521922080.4998413115183.64080749831923197.22564419
#Sta/Elev= 30
       0  526.17    32.4  523.81    66.9  522.42     136  521.97   343.1  523.47
   446.6  525.64   688.2  522.36   764.9  523.74   962.9  525.28  1031.3524.0327
  1102.5  516.72    1275  516.72  1309.6  529.56  1319.3529.9786  1380.9  532.22
  1413.1  534.27  1516.7  544.57  1566.8  548.25  1688.9  554.18  1723.8  559.31
  1792.8  573.39  1809.5  573.56  1842.9  570.93  1861.9  570.58  1896.4   573.6
  1965.4  577.58  1999.9  578.76    2069  586.73    2138  593.29  2257.8  592.37
#Mann= 3 , 0 , 0
       0     .06       0  1031.3    .035       0  1319.3     .06       0
Bank Sta=1031.3,1319.3
XS Rating Curve= 0 ,0
Exp/Cntr(USF)=0,0
Exp/Cntr=0.3,0.1

Type RM Length L Ch R = 1 ,2245    ,437.8,841.3,958.7
XS GIS Cut Line= 3
17161.84080118071921745.48210044 16539.6649967161922160.26597009
14768.85693785521922096.45306706
#Sta/Elev= 30
       0  527.94    75.1  522.86   125.1  521.89   593.8  523.86     702  521.31
   747.8  522.59   769.7   523.9   859.8  525.36   926.2524.8326   949.8  524.99
   979.8     518  1009.9   516.8  1039.9  516.72    1220  516.72    1250  521.94
  1281.9  523.48  1310.1  523.39  1343.4  521.44  1398.8  521.04  1430.1  523.16
  1460.2  524.29  1490.2  522.86  1633.2  524.87  1730.3  527.54  1850.4  529.31
  2052.8   529.9  2120.6  528.51  2210.6  527.72  2330.7  529.84  2519.7  530.14
#Mann= 3 , 0 , 0
       0     .06       0   926.2    .035       0  1281.9     .06       0
Bank Sta=926.2,1281.9
XS Rating Curve= 0 ,0
Exp/Cntr(USF)=0,0
Exp/Cntr=0.3,0.1

Type RM Length L Ch R = 1 ,1404    ,,,
XS GIS Cut Line= 2
17241.60692995821921458.3240368415024.10854994321921139.25952173
#Sta/Elev= 30
       0  526.91    34.2  527.45    94.8  523.84   185.8  523.38   246.4  521.96
   276.7   523.1   337.3  523.43   428.2  522.65   731.3  522.82   852.6  524.13
   920.8523.4313   943.5  523.47   968.6  517.15   973.8  516.53  1155.7  516.53
    1186  518.93  1216.3  523.86  1226.2523.8113  1246.6  523.74  1276.9  525.05
  1307.2  524.84  1337.5  526.54  1428.4  526.47    1580  525.47  1640.6  522.22
  1731.5  521.02  1763.5  521.88  1792.1  523.55  2034.6  527.14  2240.3  527.42
#Mann= 3 , 0 , 0
       0     .06       0   920.8    .035       0  1226.2     .06       0
Bank Sta=920.8,1226.2
XS Rating Curve= 0 ,0
Exp/Cntr(USF)=0,0
Exp/Cntr=0.3,0.1

River Reach=Wabash          ,Upper
Reach XY= 9
22505.2361867186 1924472.223926121571.97248002261923998.41312116
20882.79312738561923524.6023162220251.04538746841922993.35989856
19805.95038889031922390.3279650119332.13958395241921873.44345053
18642.96023131541921299.1273233317838.91765323891920753.52700249
 16891.296043363 1920107.4213594

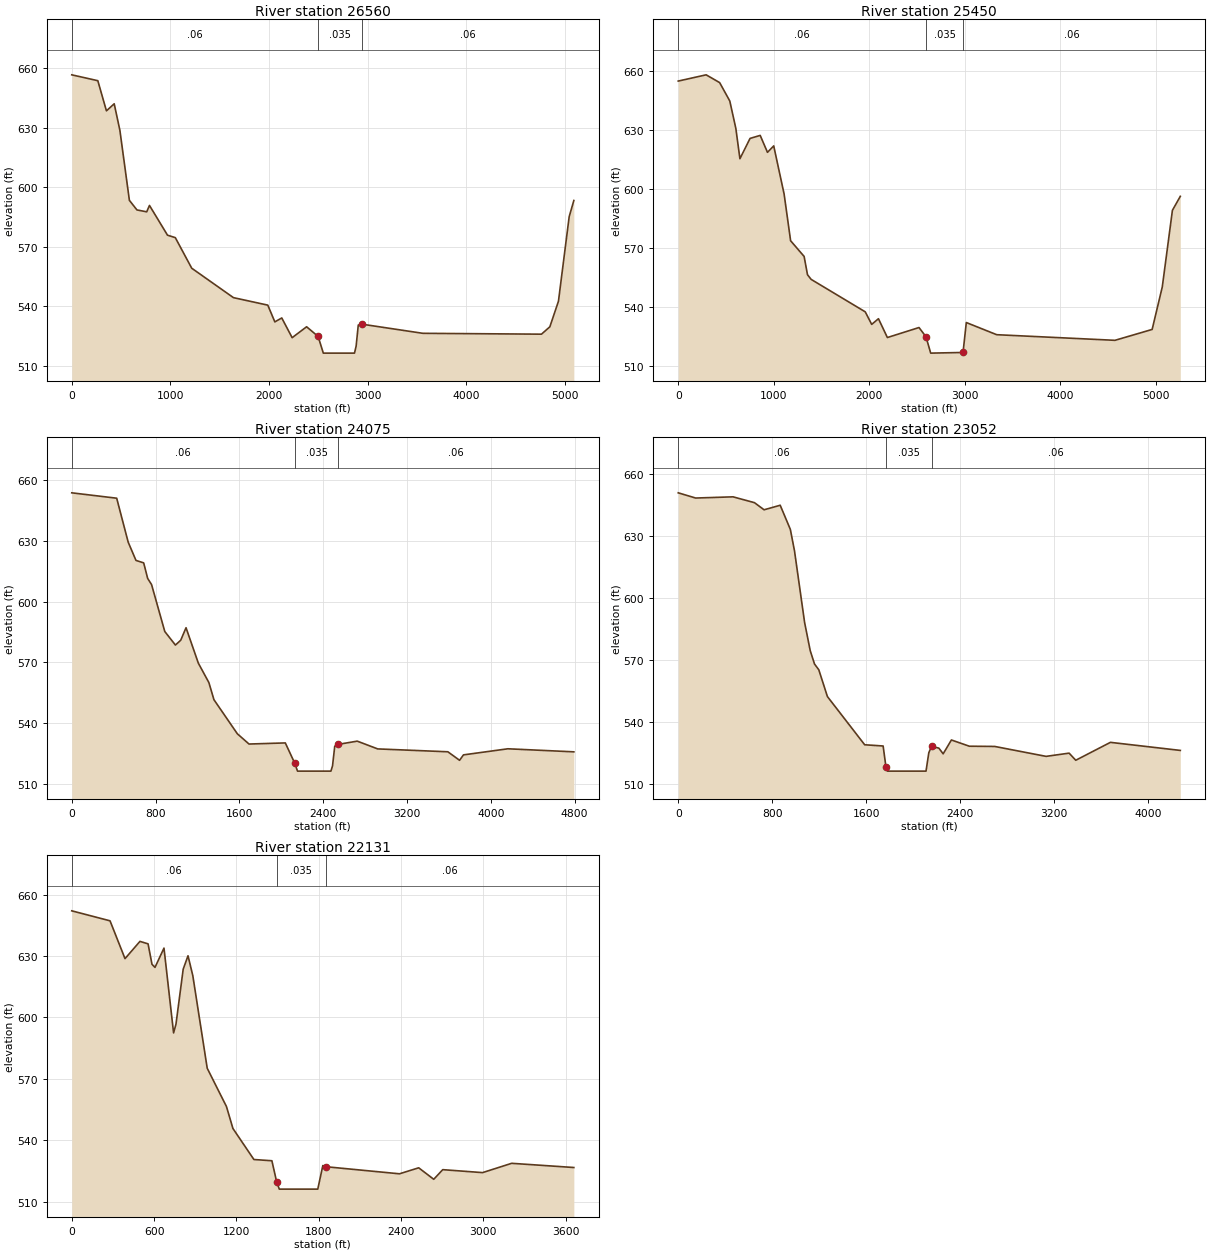
Type RM Length L Ch R = 1 ,26560   ,1087.6,1109.4,1135.8
XS GIS Cut Line= 2
23191.50524642861921786.1712148820543.84631225651926135.89660673
#Sta/Elev= 30
       0   656.6   264.2  653.64   351.6  638.45   430.4  642.01   488.1  628.63
   584.5  593.35   661.2  588.52   760.1  587.58   788.2  590.79   970.9  575.81
  1050.2  574.57  1216.7  559.16  1639.6  544.34  1988.2  540.56  2059.6  532.12
  2129.9   534.1  2235.2  524.16  2381.9  529.66  2498.6524.7825  2551.3  516.38
  2867.4  516.38    2884   519.9  2905.9  530.54    2943530.9637  3560.8  526.36
  4763.9  525.93  4848.9  529.65  4936.2  542.54  5044.9  585.12  5092.2  593.28
#Mann= 3 , 0 , 0
       0     .06       0  2498.6    .035       0    2943     .06       0
Bank Sta=2498.6,2943
XS Rating Curve= 0 ,0
Exp/Cntr(USF)=0,0
Exp/Cntr=0.3,0.1

Type RM Length L Ch R = 1 ,25450   ,1206.9,1374.8,1465.3
XS GIS Cut Line= 2
22326.96355363771921137.76494528 19544.2199799671925595.55804874
#Sta/Elev= 30
       0  654.85     292  658.03   433.5  654.07   539.6  644.71   602.9  630.76
   645.7  615.32   751.8  625.66   857.9  627.19   934.1  618.56   999.4  621.85
  1108.2  597.34  1176.2  573.56  1317.6  565.57    1353  556.26  1391.3  553.88
  1957.4  537.36  2024.9  530.97  2095.7  533.86  2189.1  524.28    2520  529.37
    2593524.6807  2642.4  516.34  2980.9516.6746  3015.2  531.91  3333.5  525.72
  4571.2  522.86  4960.3   528.4  5066.4  550.03  5172.5  589.04  5255.1  596.17
#Mann= 3 , 0 , 0
       0     .06       0    2593    .035       0  2980.9     .06       0
Bank Sta=2593,2980.9
XS Rating Curve= 0 ,0
Exp/Cntr(USF)=0,0
Exp/Cntr=0.3,0.1

Type RM Length L Ch R = 1 ,24075   ,1045.4,1023.4,959.8
XS GIS Cut Line= 2
21273.30336554881920651.4602430918436.52593607861924514.88093275
#Sta/Elev= 30
       0  653.85   428.9  651.19   538.5  629.49   612.9  620.45   686.5  619.23
   724.6  611.55   761.8  608.51     888  585.31   989.4  578.62  1040.1  580.99
  1090.8  587.18  1208.4  569.66  1308.8   560.1  1357.3  551.61  1580.6  534.77
  1692.2   529.7  2038.5  530.25  2128.2520.2728  2155.2  516.31  2473.8  516.31
  2489.2  518.87  2510.6  528.65  2544.8529.5479  2725.2  531.13  2920.5  527.29
  3590.4  525.87  3702.1  521.66  3739.3  524.34  4163.1  527.35    4793  525.84
#Mann= 3 , 0 , 0
       0     .06       0  2128.2    .035       0  2544.8     .06       0
Bank Sta=2128.2,2544.8
XS Rating Curve= 0 ,0
Exp/Cntr(USF)=0,0
Exp/Cntr=0.3,0.1

Type RM Length L Ch R = 1 ,23052   ,993.7,921.6,823.6
XS GIS Cut Line= 2
 20300.6939611591920192.1724687917869.17045018461923704.37309576
#Sta/Elev= 30
       0  650.91   148.3  648.39   466.2  648.97   648.7  646.15   730.4   642.7
   867.6   644.9   953.9  633.22   989.1  622.89  1075.4  588.12    1123  574.56
  1159.5   568.1    1196  565.31  1269.4  552.34  1586.3  529.03  1743.3  528.44
  1767.2518.3742  1779.8  516.28  2108.2  516.28  2131.9  525.16  2155.1528.2855
  2217.6   527.4  2254.1  524.65  2324.2  531.35  2476.8  528.33  2692.5  528.22
  3129.8  523.42  3325.6  524.98  3382.4  521.54  3677.1   530.2  4271.8   526.3
#Mann= 3 , 0 , 0
       0     .06       0  1767.2    .035       0  2155.1     .06       0
Bank Sta=1767.2,2155.1
XS Rating Curve= 0 ,0
Exp/Cntr(USF)=0,0
Exp/Cntr=0.3,0.1

Type RM Length L Ch R = 1 ,22131   ,,,
XS GIS Cut Line= 2
 19355.101484669 1919759.901622417463.91653168891922893.86525876
#Sta/Elev= 30
       0  652.06     279  647.18   388.2  628.72   497.1  637.15   556.2  635.94
   584.9  625.97   606.7  624.45   672.3  633.87   742.3  592.48   759.7  596.73
   812.4   623.6   847.5  630.12   882.5  620.41   987.6  575.21  1127.8  556.53
  1174.9  545.82  1327.9  530.67    1459  530.07  1494.7 519.496  1513.2  516.22
  1793.5  516.22  1830.5  527.73  1851.8527.1601  2389.2   523.7  2529.3  526.63
    2639  521.02  2704.5  525.72  2994.9  524.28  3207.2  528.82  3660.4  526.77
#Mann= 3 , 0 , 0
       0     .06       0  1494.7    .035       0  1851.8     .06       0
Bank Sta=1494.7,1851.8
XS Rating Curve= 0 ,0
Exp/Cntr(USF)=0,0
Exp/Cntr=0.3,0.1

River Reach=Wabash          ,Lower
Reach XY= 19
16896.82740392541920112.1520381816531.86876932971919791.79945893
16179.07542255391919747.1934035915643.80275848021919848.57080209
 15157.1912456861919751.2484995314419.16378461471919366.01438523
13932.55227182041919074.0474775613119.11431108741918533.60664936
12308.60647409621917696.0818844711633.18327660351917317.84489388
10822.67543961221916804.52326378 10045.906342182 1916253.0510298
9035.535377667111915632.647805987617.470866067191914391.84135833
5972.423634717871912871.782540524432.458744434471911385.85150603
3270.730844746991909683.785048352784.426142552231908603.10793236
 2379.17222405661907279.27846528

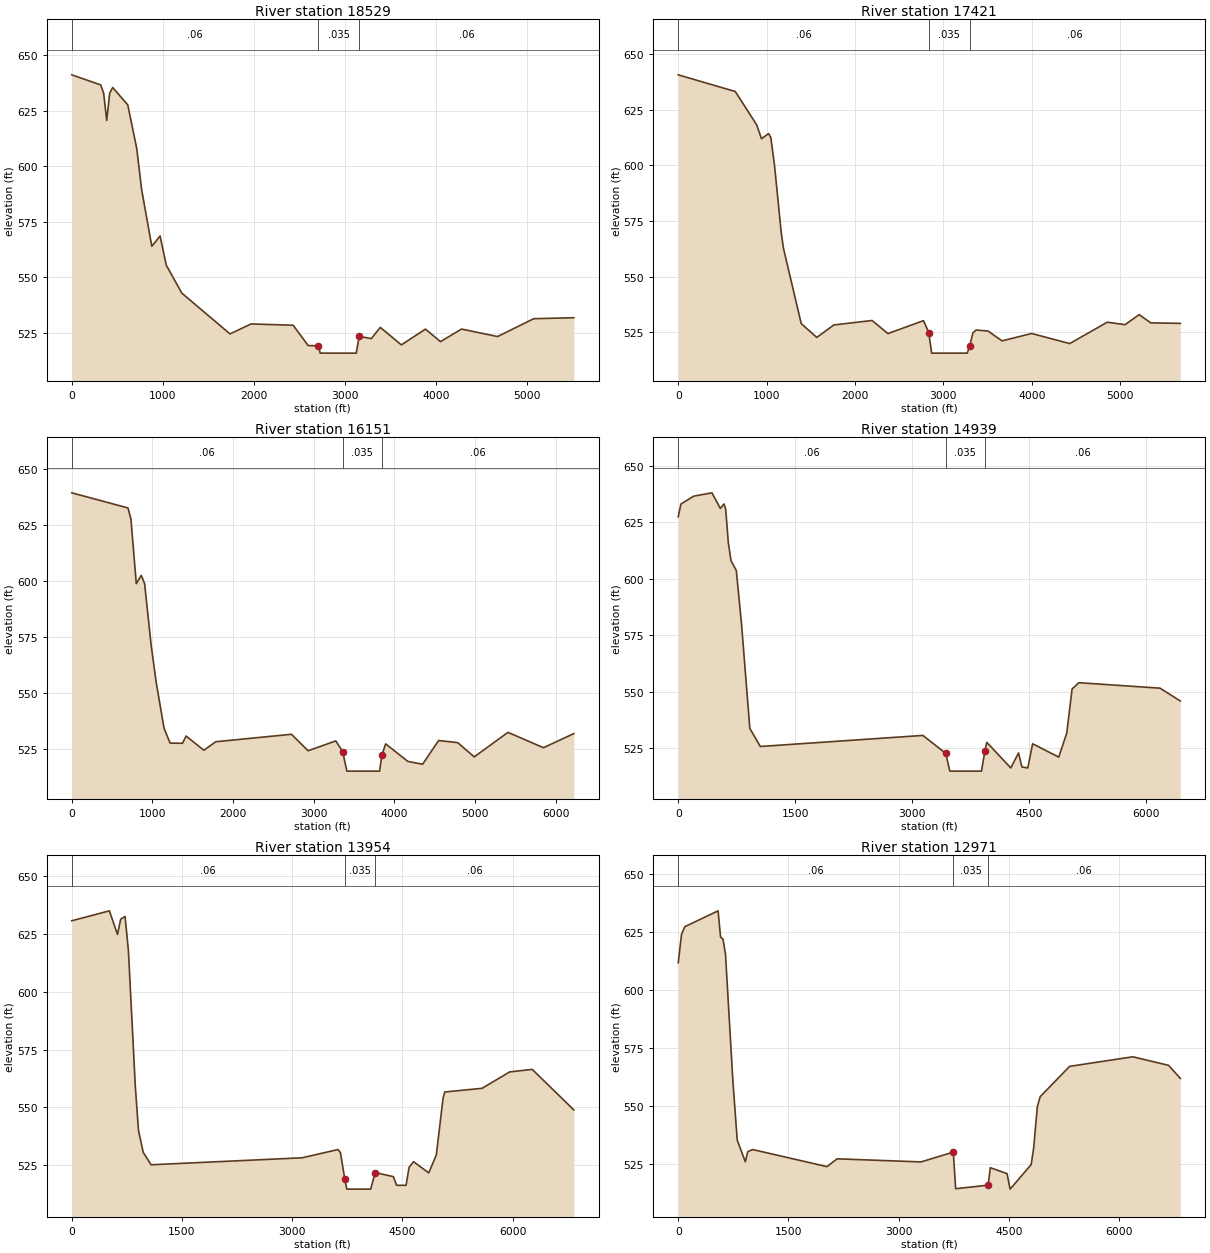
Type RM Length L Ch R = 1 ,18529   ,1067.4,1107.9,1156.5
XS GIS Cut Line= 2
16587.52467398261917166.9063086114274.30693943461922176.21919584
#Sta/Elev= 30
       0  641.26   317.9  636.71   350.9  632.92     384  620.67     417     633
     450  635.54   615.3  627.72   714.4  607.94   767.4  589.58   879.6  563.91
   970.8  568.56  1038.6  555.39  1210.1  542.77  1738.8  524.39  1970.1  528.88
  2432.7  528.31  2597.9  519.13  2709.4519.0314  2730.1  515.72  3126.6  515.72
  3158.6523.2879  3291.8  522.27    3391  527.33  3622.3  519.44  3886.9  526.56
  4051.9   520.9  4283.2  526.58  4679.7   523.2  5076.2  531.25  5517.6  531.69
#Mann= 3 , 0 , 0
       0     .06       0  2709.4    .035       0  3158.6     .06       0
Bank Sta=2709.4,3158.6
XS Rating Curve= 0 ,0
Exp/Cntr(USF)=0,0
Exp/Cntr=0.3,0.1

Type RM Length L Ch R = 1 ,17421   ,1229.9,1270.4,1344.6
XS GIS Cut Line= 2
15756.38130746131916570.7283535313215.68239084411921652.12618676
#Sta/Elev= 30
       0  640.74   645.4  633.24   888.6   618.2   941.7  612.01  1022.7  614.32
  1047.9  612.51  1089.8   599.9  1165.3  569.86  1190.4  562.81  1391.7  528.89
  1567.8  522.68  1760.6  528.29  2193.9  530.29  2372.8   524.4  2775.3  530.23
  2834.6524.8788  2867.5  515.62    3270  515.62    3297518.6498  3334.3   524.7
  3370.6  526.01  3504.8  525.56  3664.1  521.13  3999.5  524.45    4430  519.91
  4854.8  529.53  5056.1  528.41  5215.4  532.92  5346.7  529.23  5681.2     529
#Mann= 3 , 0 , 0
       0     .06       0  2834.6    .035       0    3297     .06       0
Bank Sta=2834.6,3297
XS Rating Curve= 0 ,0
Exp/Cntr(USF)=0,0
Exp/Cntr=0.3,0.1

Type RM Length L Ch R = 1 ,16151   ,1307.6,1212.2,1152.2
XS GIS Cut Line= 2
15047.34905166111915526.8753102712014.2666240716 1920962.7892714
#Sta/Elev= 30
       0  639.47   696.9   632.7   733.7  627.78     800  598.82   861.2  602.54
   903.1  598.87   984.3  571.27  1045.9  554.92  1143.5  534.26  1218.8  527.53
  1373.2  527.47  1417.3   530.7  1637.8  524.34  1784.7  528.14  2723.8  531.48
    2930  524.12  3273.5  528.51  3358.4523.7067  3410.9     515  3816.5     515
  3845.1522.1777  3891.9  527.19  4166.7  519.34    4350  518.09  4548.5   528.7
  4785.1  527.74  4989.5  521.38  5408.4  532.34  5848.3  525.47  6224.8  531.79
#Mann= 3 , 0 , 0
       0     .06       0  3358.4    .035       0  3845.1     .06       0
Bank Sta=3358.4,3845.1
XS Rating Curve= 0 ,0
Exp/Cntr(USF)=0,0
Exp/Cntr=0.3,0.1

Type RM Length L Ch R = 1 ,14939   ,998.9,985.1,997.1
XS GIS Cut Line= 2
14200.4494127887 1914581.498969211108.28096388251920234.06167516
#Sta/Elev= 30
       0  627.39    34.4  633.02   198.3   636.5   432.3  637.97   540.3  631.08
     587  633.04   609.1  630.71   642.9  615.91   677.1  607.99   745.4  603.62
   813.8  579.36   918.6  533.89  1053.2  525.86  3139.1  530.75    3433522.8461
  3485.4  514.97  3891.4  514.97  3935.5523.9142  3959.8  527.69  4267.6  516.38
  4366.8  522.99    4411  516.79  4485.6  516.38  4548.1  527.06  4883.1  521.17
  4985.7  531.75  5054.1  551.26  5140.4  554.05  6182.5  551.64  6443.1  545.97
#Mann= 3 , 0 , 0
       0     .06       0    3433    .035       0  3935.5     .06       0
Bank Sta=3433,3935.5
XS Rating Curve= 0 ,0
Exp/Cntr(USF)=0,0
Exp/Cntr=0.3,0.1

Type RM Length L Ch R = 1 ,13954   ,1122.7,983,899.1
XS GIS Cut Line= 2
13511.1124974275 1913872.466713410182.59996325461919840.15486638
#Sta/Elev= 30
       0  630.66   511.9  634.96   622.2  624.77   666.3  631.37   725.5  632.52
   770.6  617.94   864.7  559.23     908  540.09   971.8  530.64  1079.8  525.24
    3136  528.26  3621.8  531.81  3656.1  530.56  3715.2519.2013  3743.3  514.72
  4068.3  514.72  4128.8521.8953  4377.5   520.1  4420.7  516.38  4549.2  516.38
  4591.4  524.19  4652.3  526.56  4858.4  521.74  4961.4  529.44  5054.5  554.27
  5076.6  556.69  5583.7  558.27  5960.4  565.36  6266.8  566.46  6833.2  548.94
#Mann= 3 , 0 , 0
       0     .06       0  3715.2    .035       0  4128.8     .06       0
Bank Sta=3715.2,4128.8
XS Rating Curve= 0 ,0
Exp/Cntr(USF)=0,0
Exp/Cntr=0.3,0.1

Type RM Length L Ch R = 1 ,12971   ,1099.6,1218.1,1301.4
XS GIS Cut Line= 2
12585.43149679951913222.520478929473.567707454431919308.38067453
#Sta/Elev= 30
       0  611.87    45.1  624.14    89.7  627.41   542.4  634.25   576.1  622.98
   609.8  621.97   643.5  615.53   744.6  560.63   803.1  535.48   913.1  526.18
   946.8  530.52  1014.2  531.42    2025  524.07  2163.1  527.43  3305.4   526.1
  3737.1530.2483    3746  529.71  3777.1  514.56    4219516.0927  4248.8   523.6
  4475.9  521.08  4518.4  514.38  4805.4  524.98  4838.4  531.99    4889  549.89
  4927.6   554.2  5328.9  567.26  6189.2  571.38  6674.8   567.7  6835.3  562.09
#Mann= 3 , 0 , 0
       0     .06       0  3737.1    .035       0    4219     .06       0
Bank Sta=3737.1,4219
XS Rating Curve= 0 ,0
Exp/Cntr(USF)=0,0
Exp/Cntr=0.3,0.1

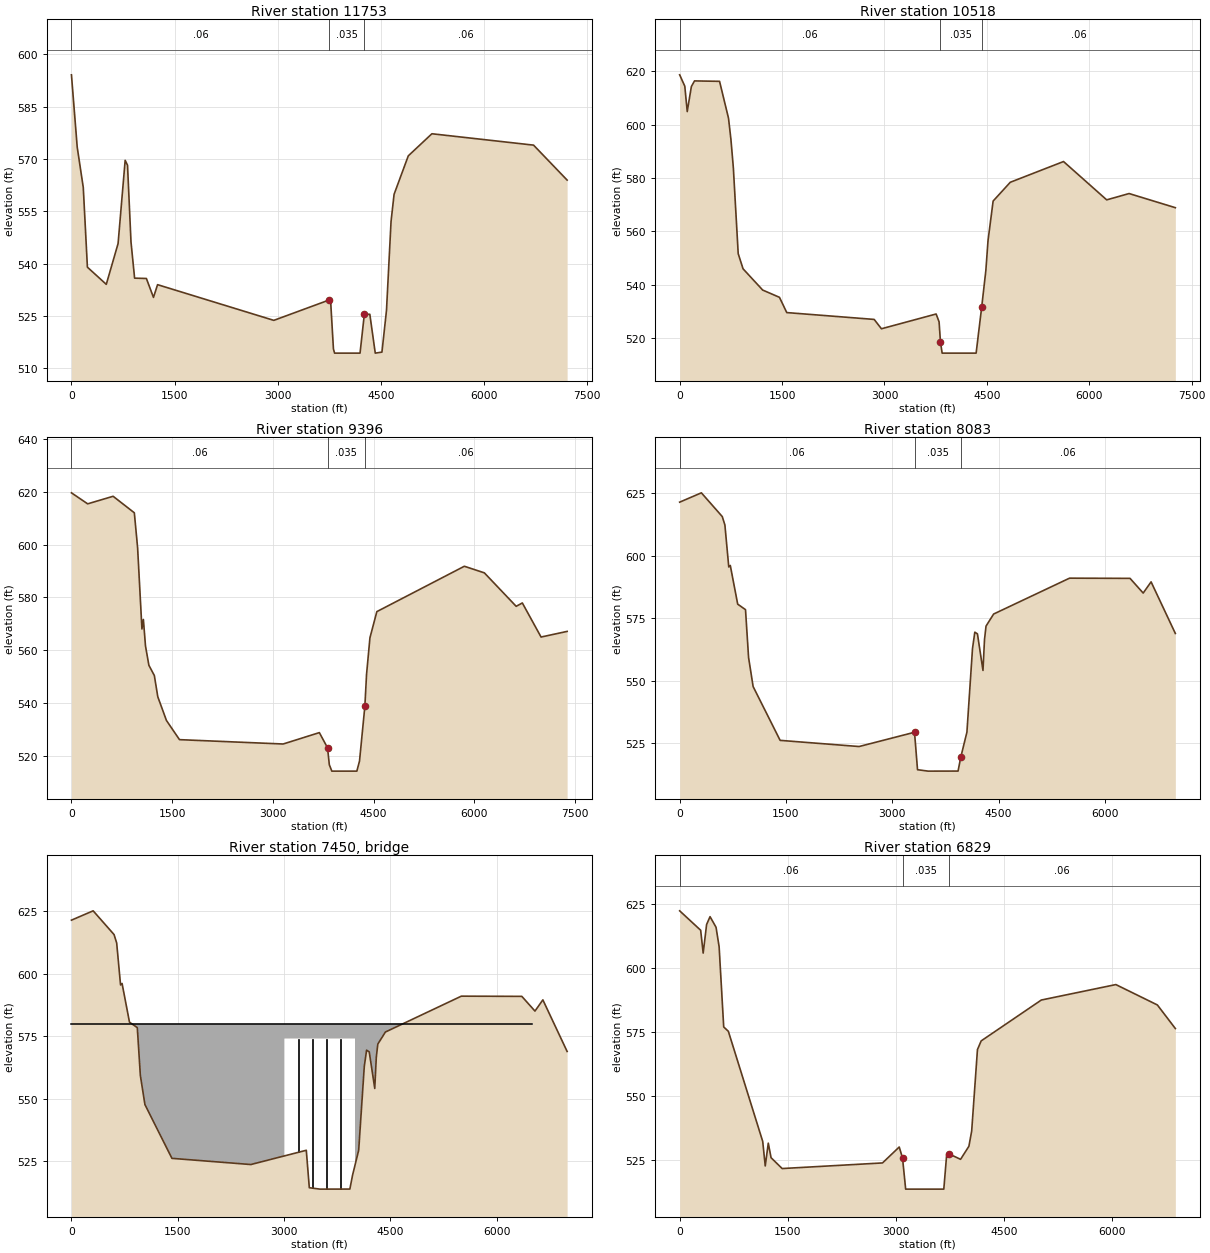
Type RM Length L Ch R = 1 ,11753   ,1016.3,1234.9,1381.9
XS GIS Cut Line= 2
11718.83651748821912572.574244438213.065919365281918875.08318488
#Sta/Elev= 30
       0  594.14    83.8  573.43   172.1  561.85   232.2  539.01   506.8  534.09
   678.5  545.78   781.5  569.64   815.8  568.22   866.3  546.26   918.8  535.87
  1090.4  535.77  1193.4  530.35    1253     534  2944.2  523.77    3754529.6418
  3768.1  530.25  3811.8  515.56  3828.6  514.38  4198.9  514.38  4261.3525.4887
  4341.2  525.51  4420.3  514.38  4517.6  514.67  4583.8  526.66    4650  552.12
  4694.1  559.89  4900.9  570.92  5244.2  577.25  6723.5  573.99  7211.9  563.97
#Mann= 3 , 0 , 0
       0     .06       0    3754    .035       0  4261.3     .06       0
Bank Sta=3754,4261.3
XS Rating Curve= 0 ,0
Exp/Cntr(USF)=0,0
Exp/Cntr=0.3,0.1

Type RM Length L Ch R = 1 ,10518   ,879.7,1121.6,1279.5
XS GIS Cut Line= 2
10931.02289993251911962.018690837031.345493031711918087.26956732
#Sta/Elev= 30
       0  618.68    75.2  614.43   110.8   604.9   171.5  614.29   217.5   616.4
   584.4  616.24   715.4  602.43     751  594.47   786.5   583.8   857.6  551.62
   928.8  545.95  1216.4  537.98  1462.2  535.26  1568.9  529.54  2849.2  526.98
  2955.9  523.47  3756.9  529.01  3800.3  526.07  3820.2518.5736    3845  514.34
  4342.9  514.34    4425  531.73  4485.2  545.28  4517.4  556.57  4591.9  571.35
  4843.4   578.4  5623.2  586.17  6255.8   571.8  6583.5  574.17  7261.3  568.87
#Mann= 3 , 0 , 0
       0     .06       0  3820.2    .035       0    4425     .06       0
Bank Sta=3820.2,4425
XS Rating Curve= 0 ,0
Exp/Cntr(USF)=0,0
Exp/Cntr=0.3,0.1

Type RM Length L Ch R = 1 ,9396    ,1328.4,1313.1,1294.2
XS GIS Cut Line= 2
10300.7720058879 1911390.8538181 5928.40642845371917338.84663064
#Sta/Elev= 30
       0   619.7   241.5  615.52   620.7  618.39   936.6  612.12   985.5   598.8
  1049.8  568.04  1071.3  571.67  1102.6  561.62  1153.2  554.28  1234.5  550.39
  1285.9  542.34  1414.6  533.35  1609.1  526.06  3152.8  524.41  3691.9  528.73
  3814.2522.9586  3840.8   516.5    3878  514.12  4250.4  514.12  4290.1  517.94
  4369.7538.6651  4394.9  550.82  4445.5  564.72  4548.2  574.63  5851.4  591.84
  6149.3  589.34  6623.5  576.64    6715  577.92    6994  564.99  7382.2  567.13
#Mann= 3 , 0 , 0
       0     .06       0  3814.2    .035       0  4369.7     .06       0
Bank Sta=3814.2,4369.7
XS Rating Curve= 0 ,0
Exp/Cntr(USF)=0,0
Exp/Cntr=0.3,0.1

Type RM Length L Ch R = 1 ,8083    ,1089.5,1253.6,1389.1
XS GIS Cut Line= 2
9079.660898676571910819.688945374963.334746947951916472.25165133
#Sta/Elev= 30
       0  621.33   306.2  625.06     601  615.57   638.1   612.2   692.7  595.42
   714.2  596.01   818.7  580.55   928.9  578.35   972.1  559.22  1036.3   547.6
  1417.4  526.09  2530.8  523.62    3313529.3255  3355.5  514.35  3505.8  513.79
  3927.4  513.81  3965.4 519.351  4052.3  529.38  4131.2  562.85  4163.7  569.35
  4200.8  568.66  4278.8  554.05  4300.3  566.39  4321.8  571.77  4429.2   576.6
  5499.7  590.94  6353.3  590.86  6538.8  584.98  6650.2  589.46  6992.5  568.83
#Mann= 3 , 0 , 0
       0     .06       0    3313    .035       0  3965.4     .06       0
Bank Sta=3313,3965.4
XS Rating Curve= 0 ,0
Exp/Cntr(USF)=0,0
Exp/Cntr=0.3,0.1

Type RM Length L Ch R = 3 ,7450    ,,,
Bridge Culvert--1,0,-1,-1, 0
Deck Dist Width WeirC Skew NumUp NumDn MinLoCord MaxHiCord MaxSubmerge Is_Ogee
633,50,2.6,0, 4, 4, , , 0.98, 0, 0,0,,
       0    3000    4000    6500
     580     580     580     580
             574     574
       0    3000    4000    6500
     580     580     580     580
             574     574
Pier Skew, UpSta & Num, DnSta & Num=  ,3200, 2 ,3200, 2 , 0 , 0 , 0 ,,
      10      10
  513.66     574
      10      10
  513.66     574
Pier Skew, UpSta & Num, DnSta & Num=  ,3400, 2 ,3400, 2 , 0 , 0 , 0 ,,
      10      10
  513.66     574
      10      10
  513.66     574
Pier Skew, UpSta & Num, DnSta & Num=  ,3600, 2 ,3600, 2 , 0 , 0 , 0 ,,
      10      10
  513.66     574
      10      10
  513.66     574
Pier Skew, UpSta & Num, DnSta & Num=  ,3800, 2 ,3800, 2 , 0 , 0 , 0 ,,
      10      10
  513.66     574
      10      10
  513.66     574
BR Coef=-1 , 0 , 0 ,, 0 ,,,0.8,-1,,0,
WSPro=,,,, 1 ,,,, 0 ,,,, 0 ,,,,-1 ,-1 ,-1 , 0 , 0 , 0 , 0 , 0
BC Design=,, 0 ,, 0 ,,4,3200,3200,200,10
BC Use User HTab Curves=0
BC User HTab FreeFlow(D)= 0

Type RM Length L Ch R = 1 ,6829    ,1295.5,1337,1374.8
XS GIS Cut Line= 2
8143.236166387151910291.24083753 3810.26126983071915628.67809647
#Sta/Elev= 30
       0  622.26   291.3  614.68   326.1  605.77   373.7  616.92   421.3  619.99
   504.6  615.84   547.2  608.26   610.8  576.95   675.2  575.25  1151.8  532.28
    1187   522.7  1229.1   531.6  1267.7  525.92  1421.6  521.69  2813.4  523.88
  3045.2   530.1  3090.9525.8273  3134.4  513.66  3663.5  513.66  3703.7  527.25
  3732.4  527.46    3896  525.29  4011.3  530.37  4049.9  536.27  4130.2  568.11
  4181.6   571.5  5015.9  587.45  6049.7  593.48  6625.5  585.53  6874.8  576.33
#Mann= 3 , 0 , 0
       0     .06       0  3090.9    .035       0  3732.4     .06       0
Bank Sta=3090.9,3732.4
XS Rating Curve= 0 ,0
Exp/Cntr(USF)=0,0
Exp/Cntr=0.3,0.1

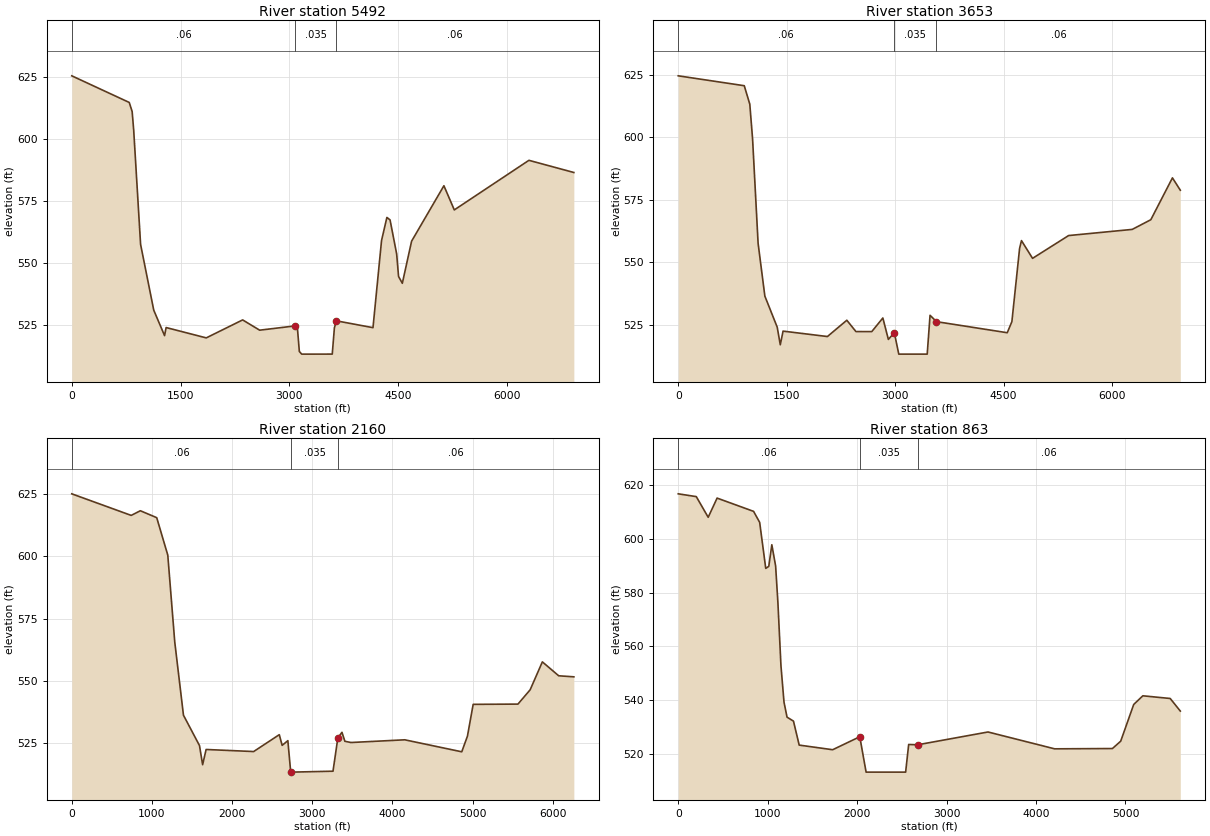
Type RM Length L Ch R = 1 ,5492    ,1320.3,1839.7,2486.5
XS GIS Cut Line= 2
7182.664304317131909437.190718412739.880605252731914750.51987202
#Sta/Elev= 30
       0  625.34   792.9  614.63   832.9  610.98   854.2  603.57   949.4  557.55
  1131.1  531.09  1280.1  520.87  1301.6  524.12  1855.2  519.96  2357.2  527.19
  2591.8  523.06  3083.3524.7891  3111.7  524.32  3139.3  514.49  3172.3  513.43
  3593.3  513.44  3622.9  523.98  3650.5526.8144  4155.3  524.07  4273.3  559.11
    4347  568.39  4390.6  567.42  4481.8  553.71    4508  544.66    4560  541.91
  4687.7  558.84  5133.6  581.14  5276.9  571.42  6306.4  591.36    6926  586.47
#Mann= 3 , 0 , 0
       0     .06       0  3083.3    .035       0  3650.5     .06       0
Bank Sta=3083.3,3650.5
XS Rating Curve= 0 ,0
Exp/Cntr(USF)=0,0
Exp/Cntr=0.3,0.1

Type RM Length L Ch R = 1 ,3653    ,1295,1492.8,1806.9
XS GIS Cut Line= 2
6372.156467325651908596.66407264938.752078604997 1912919.3725366
#Sta/Elev= 30
       0  624.53   912.9  620.58   989.6  613.22    1028  599.39  1104.6  557.59
  1197.9  536.52  1368.7  524.12  1411.4  517.08  1449.6  522.53    2063  520.37
  2331.4  526.88  2457.6  522.35  2676.4  522.34  2829.7  527.78  2905.9  519.22
  2988.2 521.929  3049.9  513.34  3443.1  513.34  3482.4  528.86  3571.5526.3111
  4549.9  521.89    4614  526.31  4720.7  555.58  4746.5   558.7  4899.9  551.61
  5398.3  560.71  6278.4  563.17  6535.5  567.04  6834.4  583.76  6943.2  578.83
#Mann= 3 , 0 , 0
       0     .06       0  2988.2    .035       0  3571.5     .06       0
Bank Sta=2988.2,3571.5
XS Rating Curve= 0 ,0
Exp/Cntr(USF)=0,0
Exp/Cntr=0.3,0.1

Type RM Length L Ch R = 1 ,2160    ,1170.2,1297.2,1492.5
XS GIS Cut Line= 2
5591.66743911164 1907726.1186181 308.357094278291911088.22520117
#Sta/Elev= 30
       0  625.13   741.2  616.46   855.6  618.33  1059.6  615.55  1197.6   600.5
  1284.5  565.59  1393.2  536.16    1593  523.96  1632.2  516.26  1675.7  522.38
  2268.6  521.55  2588.3  528.33  2624.2  524.03  2695.3  525.93  2730.9  513.28
  2739.9  513.28  3258.4  513.65  3319.1527.0839  3370.2  529.27  3406.5  525.68
  3481.9  525.18  4153.3  526.27  4864.4  521.45  4935.3  527.74  5006.7  540.52
  5565.4  540.62  5717.6  546.38  5869.7  557.59  6073.5     552  6262.4  551.58
#Mann= 3 , 0 , 0
       0     .06       0  2739.9    .035       0  3319.1     .06       0
Bank Sta=2739.9,3319.1
XS Rating Curve= 0 ,0
Exp/Cntr(USF)=0,0
Exp/Cntr=0.3,0.1

Type RM Length L Ch R = 1 ,863     ,,,
XS GIS Cut Line= 2
4691.103175787771907005.66720744-262.000272493481909647.32237985
#Sta/Elev= 30
       0  616.81   201.9  615.77     335  608.08   434.5  615.22   842.5  610.28
   910.5  606.18   978.5  589.05  1012.5  589.82  1046.5  597.86  1088.9  589.95
  1114.5  576.24  1148.5  552.83  1182.5  539.28  1216.5  533.68  1288.4  532.21
  1352.5  523.28  1726.5  521.56  2029.8526.3834  2100.5  513.22  2542.5  513.22
  2576.5  523.51  2677.9523.4026  3463.4  528.16  4208.5  521.89  4854.5     522
  4947.1  524.74  5092.5   538.4  5194.5  541.63  5500.5  540.63  5613.5  535.95
#Mann= 3 , 0 , 0
       0     .06       0  2029.8    .035       0  2677.9     .06       0
Bank Sta=2029.8,2677.9
XS Rating Curve= 0 ,0
Exp/Cntr(USF)=0,0
Exp/Cntr=0.3,0.1
LCMann Table=0

Chan Stop Cuts=-1
Use User Specified Reach Order=0
Composite Channel Slope=5